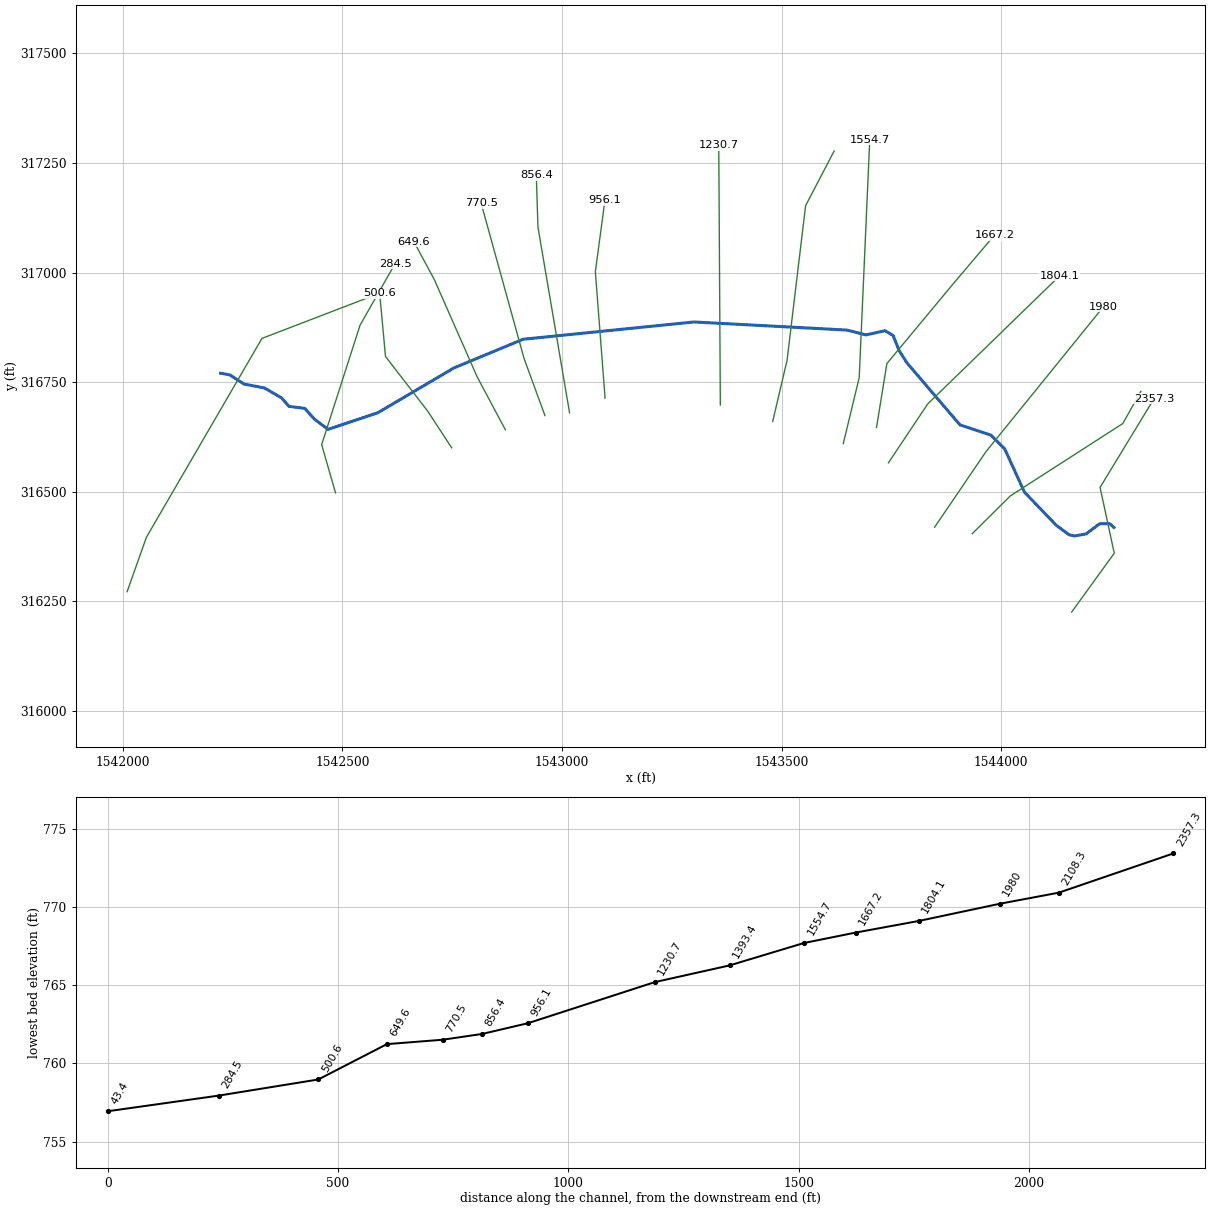
--- BRUSHRN.prj (project) ---

Proj Title=BRUSHRN
Current Plan=p01
Default Exp/Contr=0,0
English Units
Geom File=g01
Flow File=f01
Plan File=p01
BEGIN DESCRIPTION:
END DESCRIPTION:
DSS Export Rating Curves= 0
DSS Export Rating Curve Sorted= 0
DSS Export Volume Flow Curves= 0
DXF Filename=..\..\..\..\04_EngrWorking\AFG\Approximate\BRUSHRN\BRUSHRN.
DXF OffsetX= 0
DXF OffsetY= 0
DXF ScaleX= 0
DXF ScaleY= 0

--- BRUSHRN.p01 (plan) ---

Plan Title=Floodplain
Program Version=4.00
Geom File=g01
Flow File=f01
K Sum by GR=0
Std Step Tol=0.01
Critical Tol=0.01
Num of Std Step Trials=20
Max Error Tol=0.3
Flow Tol Ratio=0.001
Split Flow NTrial=30
Split Flow Tol=0.02
Split Flow Ratio=0.02
Log Output Level=0
Friction Slope Method=1
Unsteady Friction Slope Method=2
Unsteady Bridges Friction Slope Method=1
Global Log Level=0
CheckData=False
Run HTab=0
Run UNet=0
Run PostProcess=0
UNET Theta=0
UNET Theta Warmup=0
UNET ZTol=0
UNET ZSATol=0
UNET MxIter=0
UNET MaxInSteps=0
UNET DtIC=0
UNET DtMin=0
UNET MaxCRTS=0
UNET WFStab=0
UNET SFStab=0
UNET WFX=0
UNET SFX=0
UNET DSS MLevel=0
UNET DZMax Abort=0
UNET Convert EG Bridges=0
UNET Use Existing IB Tables=0
UNET Froude Limit=0
UNET Froude Power=0
Write IC File=0
Echo Input=False
Echo Output=False
Write Detailed=0

--- BRUSHRN.f01 (steady flow) ---

Flow Title=NFF Regression Equation
Program Version=4.10
Number of Profiles= 1
Profile Names=P100yr
River Rch & RM=BRUSHRN,Main            ,2357.3
     949
River Rch & RM=BRUSHRN,Main            ,500.6
     982
Boundary for River Rch & Prof#=BRUSHRN,Main            , 1
Up Type= 0
Dn Type= 3
Dn Slope=0.0001
DSS Import GetInterval= 0
DSS Import GetPeak= 0
DSS Import FillOption= 0

--- BRUSHRN.g01 (geometry) ---

Geom Title=USGS 10m DEM
Program Version=4.10

River Reach=BRUSHRN         ,Main
Reach XY= 30
     1544256.311      316418.707     1544246.749      316427.277
     1544223.854      316427.168     1544193.038      316404.056
     1544166.888       316399.39      1544154.41      316401.886
     1544124.679      316424.021      1544052.63      316499.325
     1544007.709      316597.958     1543976.459      316629.316
     1543905.929      316652.645     1543785.486      316793.813
     1543767.908      316821.157     1543753.651      316856.569
     1543735.361      316867.592     1543691.998       316857.97
     1543648.659      316869.008     1543300.243      316887.455
     1542911.571      316848.066     1542753.802      316782.528
     1542580.774      316680.429     1542467.482      316642.472
     1542436.406      316665.822     1542414.278      316690.448
     1542378.601      316694.875     1542361.413      316714.406
     1542322.394      316737.062     1542276.605      316745.595
      1542244.07      316766.584     1542222.775      316770.591

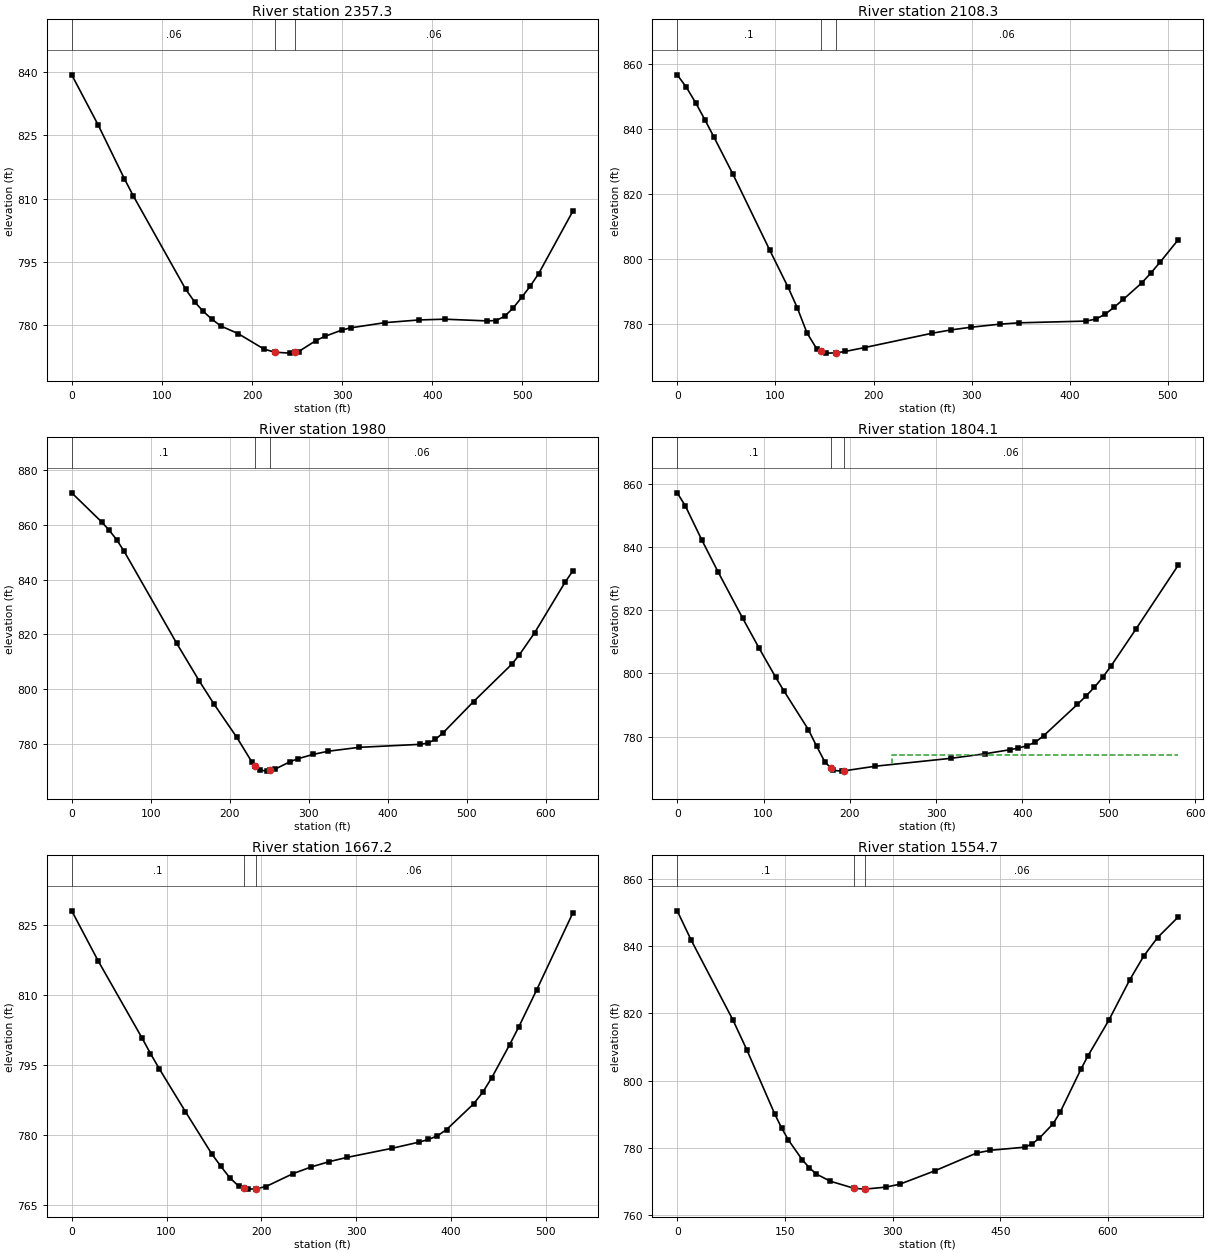
Type RM Length L Ch R = 1 ,2357.3  ,281.3,249,220.5
XS GIS Cut Line= 4
     1544160.245      316225.864     1544257.106      316359.964
     1544224.802      316510.036     1544347.745       316712.67
#Sta/Elev= 30
       0  839.27    29.2  827.46    58.4  814.69    68.1   810.7   126.5   788.5
   136.2  785.57     146  783.28   155.7  781.41   165.4  779.84   184.6  778.04
   213.4  774.36   225.6 773.632   242.2  773.42   247.6 773.636   251.8   773.8
     271   776.4   280.6  777.37   299.7  778.88   309.3   779.4   347.4  780.63
   385.3  781.27   413.7  781.45   461.1  781.04   470.6  781.14   480.1   782.1
   489.6  784.08   499.1   786.6   508.5  789.23     518  792.24     556  807.05
#Mann= 3 , 0 , 0
       0     .06       0   225.6    .045       0   247.6     .06       0
Bank Sta=225.6,247.6
XS Rating Curve= 0 ,0
Exp/Cntr=0.3,0.1

Type RM Length L Ch R = 1 ,2108.3  ,120.7,128.4,135.2
XS GIS Cut Line= 4
      1543934.03      316404.742     1544020.853      316490.922
      1544276.52      316655.754     1544317.699      316729.134
#Sta/Elev= 30
       0  856.79     9.4  852.91    18.8  848.16    28.2  842.92    37.6  837.47
    56.5  826.29    94.1  802.79   112.9  791.28   122.3  784.91   132.2  777.16
     142   772.3   146.2   771.7   151.8  770.91   161.6  770.98   171.4  771.44
     191  772.63   259.7  777.05   279.3  778.09     299  778.89   328.4  779.84
     348  780.26   416.7   780.8   426.5  781.42   435.9  782.87   445.2  785.09
   454.6  787.51   473.3  792.57   482.6  795.62     492  798.98   510.7  805.97
#Mann= 3 , 0 , 0
       0      .1       0   146.2    .045       0   161.6     .06       0
Bank Sta=146.2,161.6
XS Rating Curve= 0 ,0
Exp/Cntr=0.3,0.1

Type RM Length L Ch R = 1 ,1980    ,178.2,175.9,172.2
XS GIS Cut Line= 3
     1543848.081      316419.238     1543965.311      316591.865
     1544232.778      316922.562
#Sta/Elev= 30
       0  871.61    37.9  860.98    47.4  857.98    56.9  854.51    66.4  850.25
   132.8  816.77   161.2  803.12   180.2  794.53   208.7  782.55     228  773.48
   232.4 772.149   237.7  770.55   247.3   770.2   251.2  770.48     257   770.9
   276.3  773.64     286   774.7   305.3  776.29   324.7  777.46   363.3  778.86
   440.7  779.96   450.3   780.4     460  781.77   469.7  784.14   508.3  795.54
   556.7  809.17   566.3   812.6   585.7  820.69   624.3  839.14     634  843.22
#Mann= 3 , 0 , 0
       0      .1       0   232.4    .045       0   251.2     .06       0
Bank Sta=232.4,251.2
XS Rating Curve= 0 ,0
Exp/Cntr=0.3,0.1

Type RM Length L Ch R = 1 ,1804.1  ,133.7,136.8,139.5
XS GIS Cut Line= 3
     1543743.003      316566.157     1543832.533      316700.537
     1544132.952      316992.884
#Sta/Elev= 30
       0  857.06     9.5  852.87    28.5  842.14    47.5  831.98      76  817.35
      95  807.89     114  798.79   123.5   794.5     152   782.2   161.5  776.98
   171.2  771.94   178.4  770.03     181  769.34   190.7   769.1   193.4  769.19
   229.7  770.66   317.4  773.16   356.4  774.58   385.7  775.87   395.4  776.42
   405.2   777.1   414.9  778.25   424.7  780.32   463.7  790.21   473.4  792.79
   483.2  795.56   492.9  798.72   502.7  802.36   531.9  814.17   580.7  834.28
#Mann= 3 , 0 , 0
       0      .1       0   178.4    .045       0   193.4     .06       0
#XS Ineff= 2 , 0
                           249.4          774.19
Permanent Ineff=
       F       F
Bank Sta=178.4,193.4
XS Rating Curve= 0 ,0
Exp/Cntr=0.3,0.1

Type RM Length L Ch R = 1 ,1667.2  ,95.1,112.5,126.8
XS GIS Cut Line= 4
      1543715.92      316646.712     1543739.531      316792.545
     1543891.614      316975.879     1543983.975      317084.907
#Sta/Elev= 30
       0  827.97    27.7  817.32    73.9  800.83    83.1   797.4    92.3  794.16
     120  784.95   147.7  775.92   157.3  773.26   166.8  770.78   176.3  768.98
     182  768.61   185.8  768.36     194 768.411   204.9  768.91   233.5  771.68
   252.5   773.1   271.6  774.24   290.6  775.16   338.3  777.12   366.9  778.45
   376.4     779   385.9  779.78   395.5  781.12     424  786.62   433.6  789.09
   443.1   792.2   462.1  799.32   471.7  803.12   490.7   811.1   528.8  827.56
#Mann= 3 , 0 , 0
       0      .1       0     182    .045       0     194     .06       0
Bank Sta=182,194
XS Rating Curve= 0 ,0
Exp/Cntr=0.3,0.1

Type RM Length L Ch R = 1 ,1554.7  ,162.8,161.3,159.4
XS GIS Cut Line= 3
     1543640.225      316609.907     1543676.532      316760.562
     1543700.552      317303.228
#Sta/Elev= 30
       0  850.55    19.4  841.83    77.5  818.09    96.9   809.2   135.6  790.17
   145.3  785.95     155  782.27   174.4  776.37   184.1  774.03   193.8  772.18
   213.2  770.05   246.4  767.93   261.4  767.69   290.8  768.29   310.2  769.17
   358.7  773.13   416.9  778.42   436.3  779.25   484.8   780.2   494.5  781.19
   504.2   782.8   523.6  787.16   533.3  790.53   562.4  803.41   572.1  807.35
   601.2  817.96   630.3  829.98   649.7  837.03   669.1  842.58   698.2  848.78
#Mann= 3 , 0 , 0
       0      .1       0   246.4    .045       0   261.4     .06       0
Bank Sta=246.4,261.4
XS Rating Curve= 0 ,0
Exp/Cntr=0.3,0.1

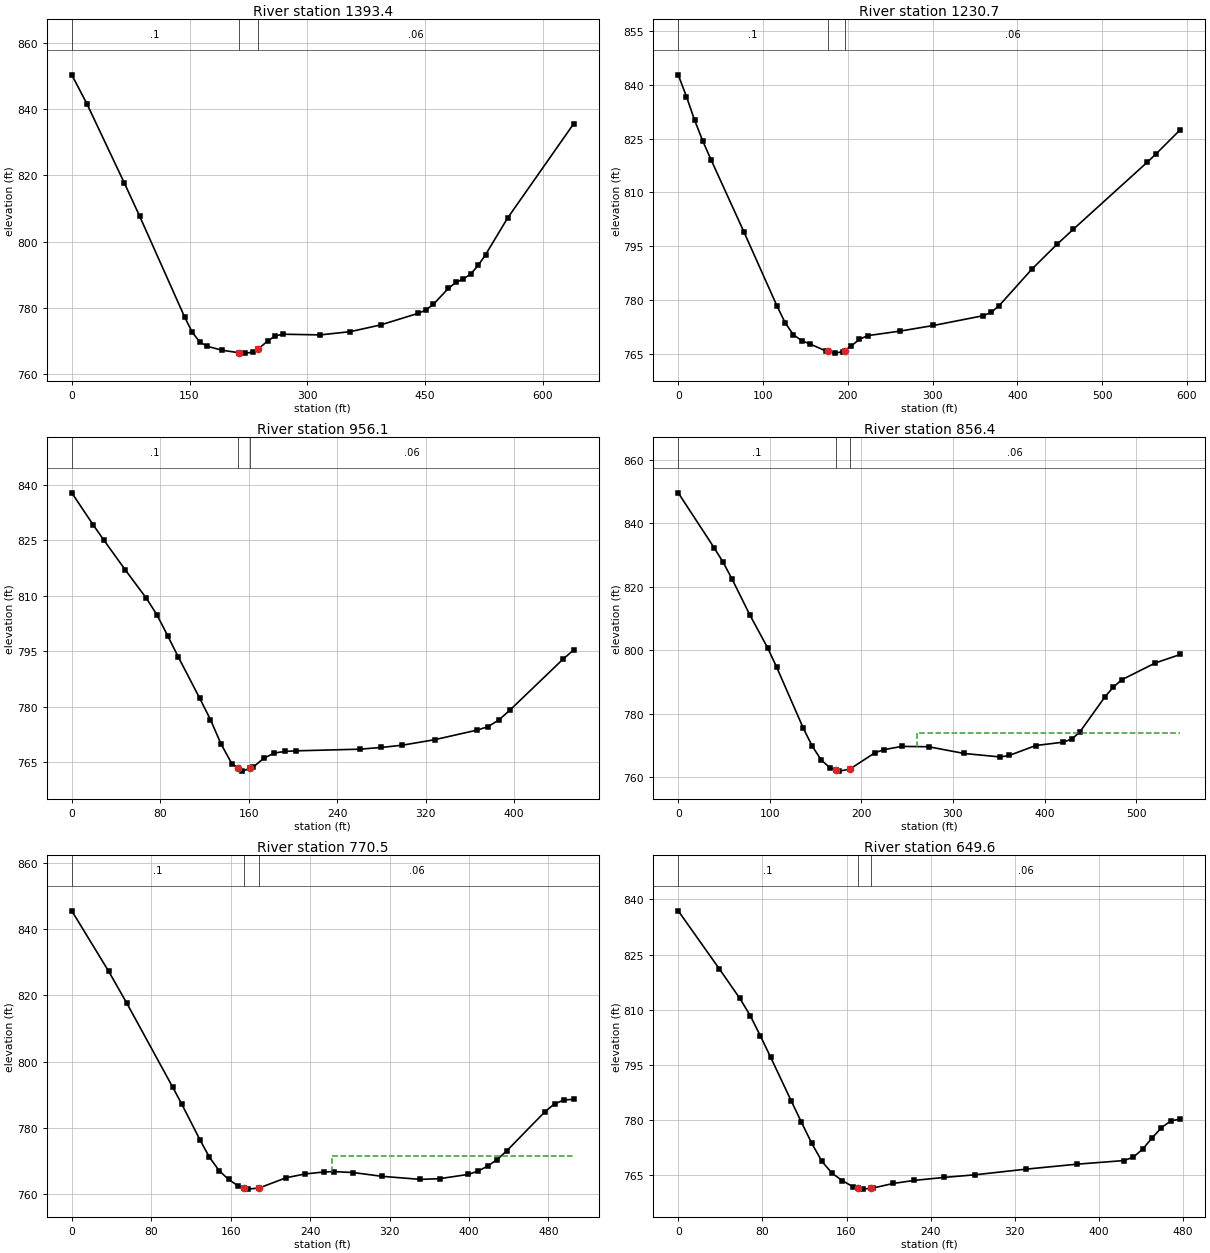
Type RM Length L Ch R = 1 ,1393.4  ,159.6,162.7,165.3
XS GIS Cut Line= 4
      1543479.54      316660.239     1543512.326      316800.229
     1543554.527      317152.818     1543619.546      317277.537
#Sta/Elev= 30
       0   850.4    19.2  841.67    67.1  817.62    86.3  807.75   143.8  777.15
   153.4   772.6     163  769.63   172.6  768.32   191.8  767.12   212.6 766.393
   220.6  766.26   230.2  766.51   237.1 767.444   249.4   769.9     259  771.43
   268.5  771.98   316.5  771.77   354.9  772.76   393.3  774.78   441.3  778.29
   450.9  779.28   460.5     781   479.7  785.84   489.3  787.65   498.9   788.7
   508.3  790.21   517.6  792.78     527     796   555.1  807.09   639.5  835.68
#Mann= 3 , 0 , 0
       0      .1       0   212.6    .045       0   237.1     .06       0
Bank Sta=212.6,237.1
XS Rating Curve= 0 ,0
Exp/Cntr=0.3,0.1

Type RM Length L Ch R = 1 ,1230.7  ,272.6,274.6,275.8
XS GIS Cut Line= 2
      1543360.39      316698.186     1543356.854      317290.359
#Sta/Elev= 30
       0   842.8     9.7  836.72    19.4   830.1    29.1  824.25    38.8  819.07
    77.7  798.88   116.5  778.33   126.2  773.62   135.9   770.3   145.6  768.68
   155.3  767.75   174.7  765.74   176.3 765.651   184.4  765.19   194.2  765.58
   196.3  765.92   203.9  767.15   213.6  769.02   223.3  770.06   262.1  771.35
     301   772.9   359.2   775.6   368.9  776.54   378.6  778.45   417.4  788.68
   446.6   795.5     466  799.73   553.4  818.47   563.1  820.64   592.2   827.5
#Mann= 3 , 0 , 0
       0      .1       0   176.3    .045       0   196.3     .06       0
Bank Sta=176.3,196.3
XS Rating Curve= 0 ,0
Exp/Cntr=0.3,0.1

Type RM Length L Ch R = 1 ,956.1   ,97.6,99.8,101.7
XS GIS Cut Line= 3
     1543098.035      316713.634     1543075.887      317002.122
     1543097.775      317165.454
#Sta/Elev= 30
       0  837.78    19.3  829.15    28.9  825.05    48.2  817.03    67.5  809.28
    77.2  804.71    86.8  799.13    96.4  793.38   115.7  782.28   125.4  776.51
     135   769.9   144.7  764.62   150.2 763.448   154.3  762.57   161.2 763.321
     164  763.63   173.6  766.03   183.2  767.47   192.9  767.89   202.5  768.05
   260.4   768.5   279.7  768.96     299  769.58   328.1  771.06   366.9  773.68
   376.6  774.61   386.3   776.4     396  778.98   444.4  792.85   454.1  795.35
#Mann= 3 , 0 , 0
       0      .1       0   150.2    .045       0   161.2     .06       0
Bank Sta=150.2,161.2
XS Rating Curve= 0 ,0
Exp/Cntr=0.3,0.1

Type RM Length L Ch R = 1 ,856.4   ,83.6,85.9,88.2
XS GIS Cut Line= 3
     1543017.205      316680.222     1542945.242      317103.768
     1542941.504      317222.355
#Sta/Elev= 30
       0  849.65    39.1  832.36    48.8  827.86    58.6  822.57    78.1  811.19
    97.6  800.78   107.4  794.73   136.7  775.33   146.5  769.68   156.2  765.38
     166  762.88   172.3  762.24   175.8  761.88   187.3   762.5   214.8  767.67
   224.6  768.64   244.1  769.68   273.4  769.57   312.4  767.44   351.5  766.35
   361.3  766.81   390.6  769.96   419.8  770.99   429.6  771.94   438.7  774.28
   466.1  785.35   475.2  788.39   484.4   790.7   520.9  795.98   548.3  798.67
#Mann= 3 , 0 , 0
       0      .1       0   172.3    .045       0   187.3     .06       0
#XS Ineff= 2 , 0
                          260.94          774.03
Permanent Ineff=
       F       F
Bank Sta=172.3,187.3
XS Rating Curve= 0 ,0
Exp/Cntr=0.3,0.1

Type RM Length L Ch R = 1 ,770.5   ,117.4,120.9,124
XS GIS Cut Line= 3
     1542961.076       316674.06     1542913.594      316804.268
     1542815.937      317158.087
#Sta/Elev= 30
       0  845.48      37  827.31    55.4  817.62   101.6  792.29   110.9  787.09
   129.4   776.2   138.6  771.16   148.3  767.12   157.9  764.42   167.6  762.49
   173.7  761.87   177.2  761.51   188.7  761.85   215.9  764.95   235.2   766.1
   254.5   766.7   264.2   766.8   283.5  766.51   312.5  765.37   351.1  764.45
   370.4  764.66   399.4  765.96     409  766.94   418.7  768.43   428.4  770.44
     438  773.05   476.7  784.92   486.3  787.26     496  788.44   505.6  788.59
#Mann= 3 , 0 , 0
       0      .1       0   173.7    .045       0   188.7     .06       0
#XS Ineff= 2 , 0
                          262.53          771.61
Permanent Ineff=
       F       F
Bank Sta=173.7,188.7
XS Rating Curve= 0 ,0
Exp/Cntr=0.3,0.1

Type RM Length L Ch R = 1 ,649.6   ,143.2,149,154.1
XS GIS Cut Line= 4
     1542871.134      316641.473     1542806.898      316762.133
     1542709.477      316983.816     1542662.801       317070.64
#Sta/Elev= 30
       0  836.87    39.1  821.08    58.6  813.06    68.4  808.42    78.1  802.88
    87.9  797.07   107.4  785.23   117.2  779.38   126.9   773.7   136.7  768.75
   146.4   765.5   156.1  763.55   165.8  761.91     171 761.539   175.4  761.23
     183  761.46   185.1  761.52   204.5  762.78   223.9  763.58   252.9  764.42
     282  765.12   330.4  766.65   378.8     768   423.6  768.99   432.6  769.89
   441.6  772.09   450.5  775.11   459.5  777.94   468.4  779.78   477.4  780.27
#Mann= 3 , 0 , 0
       0      .1       0     171    .045       0     183     .06       0
Bank Sta=171,183
XS Rating Curve= 0 ,0
Exp/Cntr=0.3,0.1

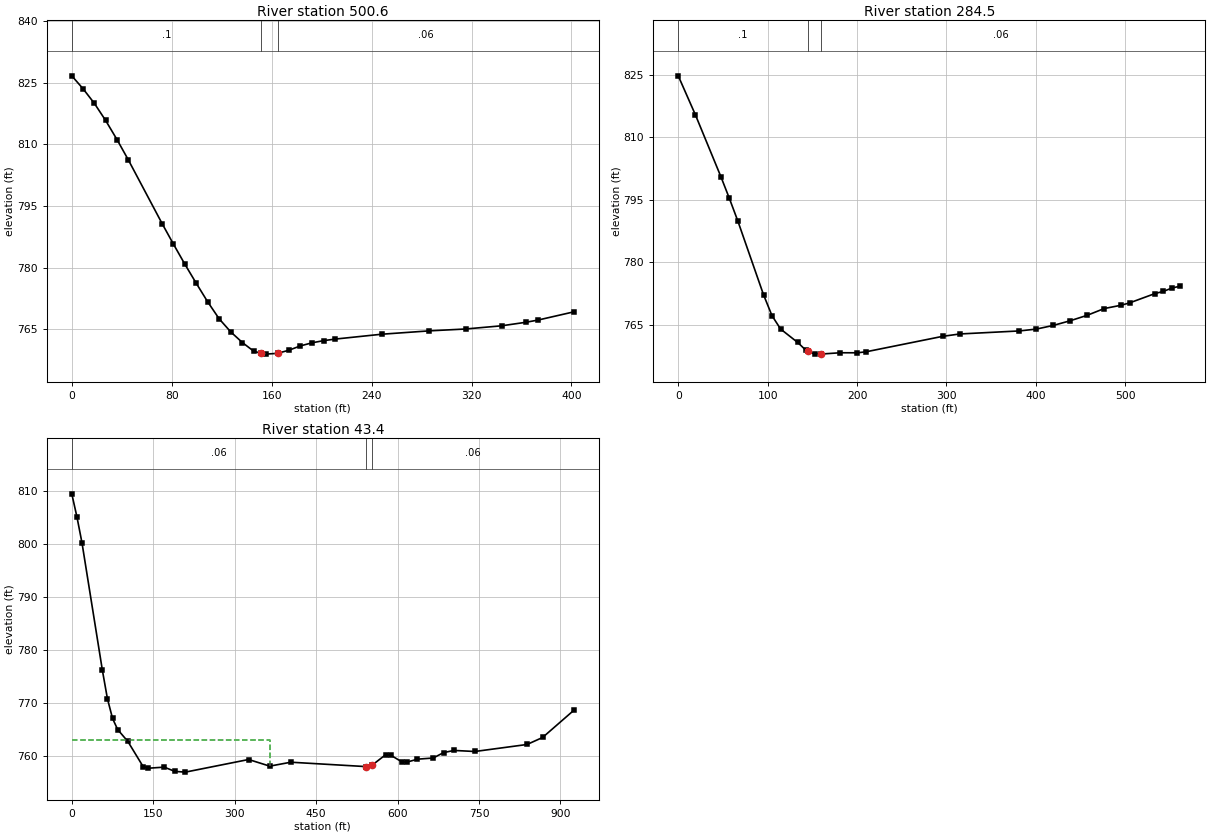
Type RM Length L Ch R = 1 ,500.6   ,238.9,216.1,191.7
XS GIS Cut Line= 4
     1542748.825      316600.414     1542694.499      316683.693
     1542598.183      316808.855     1542584.939      316952.781
#Sta/Elev= 30
       0  826.64       9  823.51    18.1  819.94    27.1  815.79    36.2  811.14
    45.2  806.24    72.3  790.72    81.4  785.71    90.4   780.9    99.4  776.32
   108.7  771.73     118  767.55   127.3  764.36   136.6  761.78   145.9  759.62
   151.7 759.212   155.2  758.97   164.7  759.16   173.8  759.92     183  760.97
   192.3  761.72   201.6  762.25   210.9  762.63   248.1  763.81   286.3  764.63
   315.2  765.08   344.1  765.86   363.4  766.71     373  767.24   401.9  769.25
#Mann= 3 , 0 , 0
       0      .1       0   151.7    .045       0   164.7     .06       0
Bank Sta=151.7,164.7
XS Rating Curve= 0 ,0
Exp/Cntr=0.3,0.1

Type RM Length L Ch R = 1 ,284.5   ,244.4,241.1,233.6
XS GIS Cut Line= 4
     1542484.415      316497.637     1542452.896      316607.671
     1542540.355      316880.326     1542619.832      317020.206
#Sta/Elev= 30
       0  824.77    19.1  815.46    47.7  800.56    57.2  795.34    66.8  789.83
    95.4  772.21   104.9  767.17   114.5  763.97   133.6  760.75   143.1  758.82
   144.9  758.65   152.6  757.94   159.9  757.96   181.3  758.27   200.4  758.26
   209.9  758.49   295.8  762.21   314.9  762.78   381.7  763.51   400.8  763.96
   419.7  764.84   438.6  765.96   457.6  767.27   476.5  768.88   495.4  769.68
   504.9  770.24   533.3  772.48   542.8  773.01   552.2   773.8   561.7  774.27
#Mann= 3 , 0 , 0
       0      .1       0   144.9    .045       0   159.9     .06       0
Bank Sta=144.9,159.9
XS Rating Curve= 0 ,0
Exp/Cntr=0.3,0.1

Type RM Length L Ch R = 1 ,43.4    ,33.4,43.4,52.8
XS GIS Cut Line= 4
     1542010.078       316272.28     1542053.898      316396.253
     1542316.975      316849.966     1542567.716       316946.45
#Sta/Elev= 30
       0  809.41     9.4  805.12    18.8  800.18    56.4  776.12    65.7  770.76
    75.1  767.06    84.5  764.97   103.3  762.72   131.5  757.97   141.2  757.68
   170.3  757.88   189.8  757.08   209.2  756.94   325.7  759.32   364.6  758.07
   403.4  758.81   541.1 757.987   553.1  758.25   578.3  760.25     588   760.1
   607.4   758.9   617.1  758.82   636.5  759.38   665.6   759.6   684.7  760.62
   703.9  761.03   742.3  760.83   838.3  762.15     867  763.47   924.6   768.6
#Mann= 3 , 0 , 0
       0     .06       0   541.1    .045       0   553.1     .06       0
#XS Ineff= 2 , 0
       0     365     763               0
Permanent Ineff=
       F       F
Bank Sta=541.1,553.1
XS Rating Curve= 0 ,0
Exp/Cntr=0.3,0.1

Chan Stop Cuts=-1
Use User Specified Reach Order=0
Composite Channel Slope=5